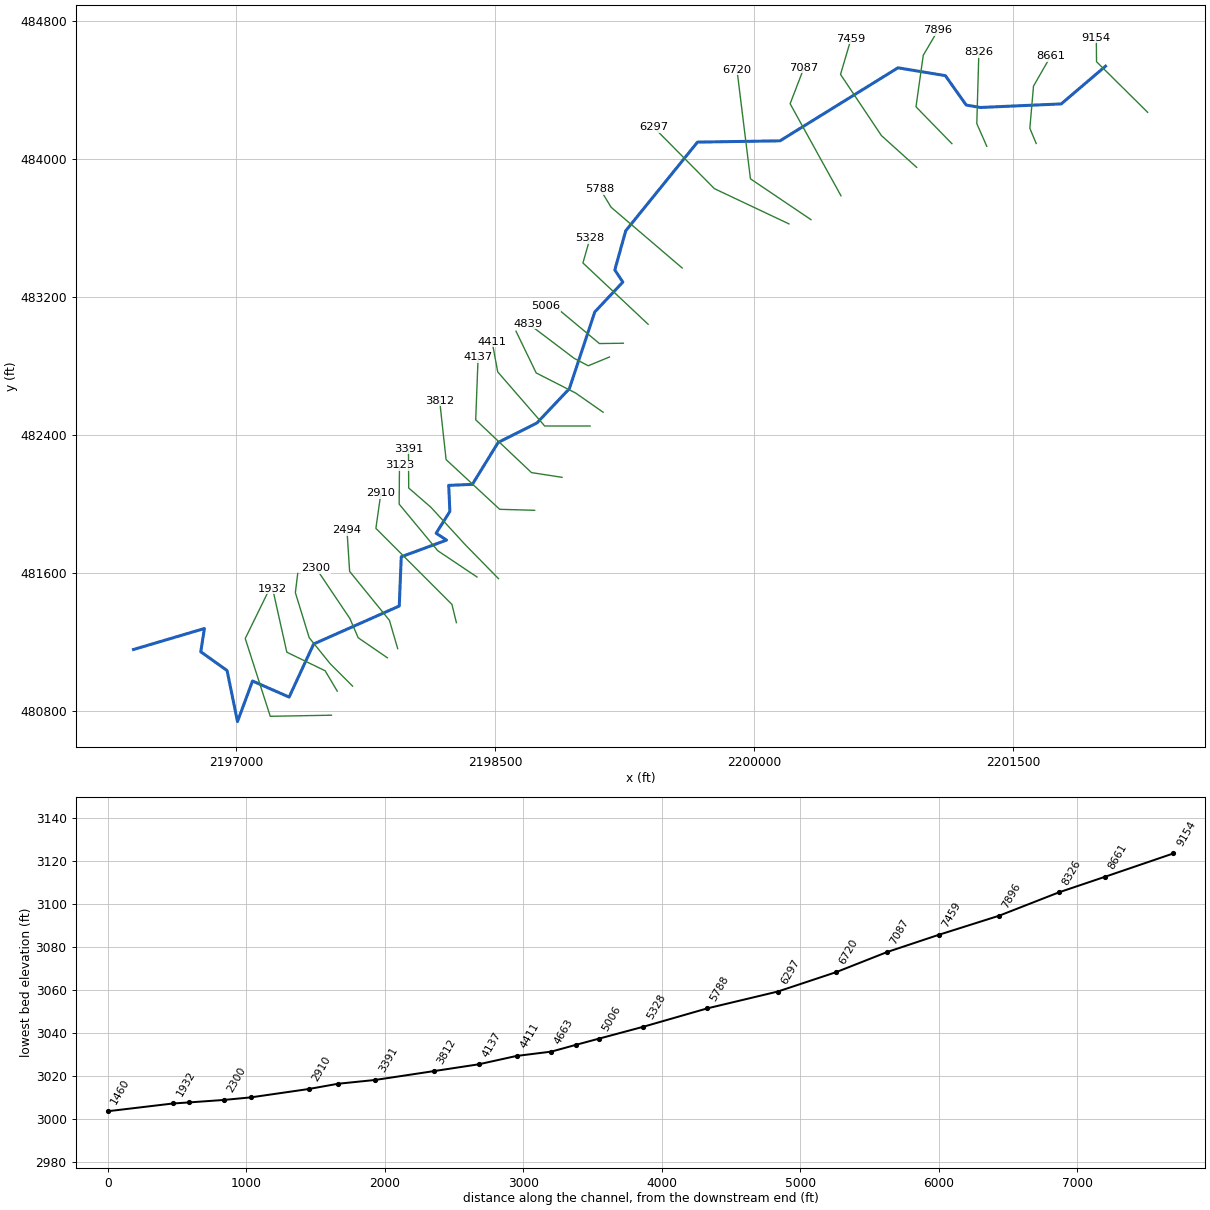
--- LTTLLAURLCK.prj (project) ---

Proj Title=LTTLLAURLCK
Current Plan=p01
Default Exp/Contr=0,0
English Units
Geom File=g01
Flow File=f01
Plan File=p01
BEGIN DESCRIPTION:
----------MODEL BY WOOD PLC 2021----------
Stream Name: Little Laurel Creek
Flood Zone: Approximate
Pocahontas County, WV
HEC-RAS Version: RAS 6.0
Vertical Datum: NAVD88
Projection: NAD 1983 StatePlane West Virginia S FIPS 4702 (US Feet)
Terrain: 1-meter LIDAR (FEMA Region III 3DEP collected 2016-2018)
Land Use: 2016 NLCD
Hydrologic Method:
WV SIR2010-5033 regression equations
END DESCRIPTION:
DSS Export Rating Curves= 0
DSS Export Rating Curve Sorted= 0
DSS Export Volume Flow Curves= 0
DXF OffsetX= 0
DXF OffsetY= 0
DXF ScaleX= 0
DXF ScaleY= 0

--- LTTLLAURLCK.p01 (plan) ---

Plan Title=Floodplain
Program Version=6.10
Short Identifier=Floodplain
Geom File=g01
Flow File=f01
Subcritical Flow
K Sum by GR= 0
Std Step Tol= 0.01
Critical Tol= 0.01
Num of Std Step Trials= 20
Max Error Tol= 0.3
Flow Tol Ratio= 0.001
Split Flow NTrial= 30
Split Flow Tol= 0.02
Split Flow Ratio= 0.02
Log Output Level= 0
Friction Slope Method= 1
Unsteady Friction Slope Method= 2
Unsteady Bridges Friction Slope Method= 1
Parabolic Critical Depth
Global Vel Dist= 0 , 0 , 0
Global Log Level= 0
CheckData=True
Encroach Param=-1 ,0,0, 0
Mapping Interval=1HOUR
Computation Time Step Use Courant=        0
Computation Time Step Use Time Series=    0
Computation Time Step Count To Double=0
Computation Time Step Max Doubling=0
Computation Time Step Max Halving=0
Computation Time Step Residence Courant=0
Run HTab= 0
Run UNet= 0
Run Sediment= 0
Run PostProcess= 0
Run WQNet= 0
Run RASMapper= 0
UNET Theta= 0
UNET Theta Warmup= 0
UNET ZTol= 0
UNET ZSATol= 0
UNET MxIter= 0
UNET Max Iter WO Improvement= 0
UNET MaxInSteps= 0
UNET DtIC= 0
UNET DtMin= 0
UNET MaxCRTS= 0
UNET WFStab= 0
UNET SFStab= 0
UNET WFX= 1
UNET SFX= 1
UNET Gravity=32.174
UNET 1D Methodology=Finite Difference
UNET DSS MLevel= 1
UNET Pardiso=0
UNET DZMax Abort= 0
UNET Use Existing IB Tables= 0
UNET Froude Reduction=False
UNET Froude Limit= 0
UNET Froude Power= 0
UNET D1 Cores= 0
UNET WindReference=Eulerian
UNET WindDragFormulation=Hsu (1988)
UNET D2 Coriolis=0
UNET D2 Cores= 0
UNET D2 Theta= 1
UNET D2 Theta Warmup= 1
UNET D2 Z Tol= 0.01
UNET D2 Volume Tol= 0.01
UNET D2 Max Iterations= 20
UNET D2 Equation= 0
UNET D2 RampUpFraction=0.1
UNET D2 TimeSlices= 1
UNET D2 Turbulence Formulation=Non-Conservative (original)
UNET D2 Eddy Viscosity=0.3
UNET D2 Transverse Eddy Viscosity=0.1
UNET D2 Smagorinsky Mixing=0
UNET D2 BCVolumeCheck=0
UNET D2 Cores=0
UNET D2 SolverType=PARDISO (Direct)
UNET D2 Minimum Iterations= 2147483647
UNET D2 Maximum Iterations= 2147483647
UNET D2 Restart Number= 10
UNET D2 Relaxation Coeff=1.3
UNET D2 SOR Precondition Iterations= 10
UNET D2 ILUT Maximum Fill= 8
UNET D2 ILUT Tolerance=1E-08
UNET D1D2 MaxIter= 0
UNET D1D2 ZTol=0.01
UNET D1D2 QTol=0.1
UNET D1D2 MinQTol=1
Write IC File= 0
Write IC File at Fixed DateTime=0
Write IC File at Sim End=0
Echo Input=False
Echo Parameters=False
Echo Output=False
Write Detailed= 0
HDF Write Warmup=0
HDF Write Time Slices=0
HDF Flush=0
HDF Compression= 1
HDF Chunk Size= 1
HDF Spatial Parts= 1
HDF Use Max Rows=0
HDF Fixed Rows= 1
Calibration Method= 0
Calibration Iterations= 20
Calibration Max Change=0.05
Calibration Tolerance=0.2
Calibration Maximum=1.5
Calibration Minimum=0.5
Calibration Optimization Method= 1
WQ AD Non Conservative
WQ ULTIMATE=-1
WQ Max Comp Step=1HOUR
WQ Output Interval=15MIN
WQ Output Selected Increments= 0
WQ Output face flow=0
WQ Output face velocity=0
WQ Output face area=0
WQ Output face dispersion=0
WQ Output cell volume=0
WQ Output cell surface area=0
WQ Output cell continuity=0
WQ Output cumulative cell continuity=0
WQ Output face conc=0
WQ Output face dconc_dx=0
WQ Output face courant=0
WQ Output face peclet=0
WQ Output face adv mass=0
WQ Output face disp mass=0
WQ Output cell mass=0
WQ Output cell source sink temp=0
WQ Output nsm pathways=0
WQ Output nsm derived pathways=0
WQ Create Restart=0
WQ Fixed Restart=0
WQ System Summary=0
WQ Write To DSS=0
Sorting and Armoring Iterations= 10
XS Update Threshold= 0.02
Bed Roughness Predictor= 0
Hydraulics Update Threshold= 0.02
Energy Slope Method= 1
Volume Change Method= 1
Sediment Retention Method= 0
Sediment TS Multiplier= 1
Warm Up Method= 0
XS Weighting Method= 0
Number of US Weighted Cross Sections= 1
Number of DS Weighted Cross Sections= 1
Upstream XS Weight=0
Main XS Weight=1
Downstream XS Weight=0
Number of DS XS's Weighted with US Boundary= 1
Upstream Boundary Weight= 1
Weight of XSs Associated with US Boundary= 0
Number of US XS's Weighted with DS Boundary= 1
Downstream Boundary Weight= 0.5
Weight of XSs Associated with DS Boundary= 0.5
Percentile Method= 0
Sediment Output Level= 3
Mass or Volume Output= 0
Output Increment Type= 1
Profile and TS Output Increment= 1
Transport Output Increment 1
XS Output Flag= 0
XS Output Increment= 10
Read HDF5 Sediment Hotstart= 0
Sediment Hotstart Type= 0
Write Gradation File= 0
Read Gradation Hotstart= 0
Write HDF5 File= 1
Write Binary Output= 1
Write DSS Sediment File= 0
DSS Sediment Output Type= 1
SV Curve= 0
Specific Gage Flag= 0
Subcell Erosion Methods= 0
Subcell Deposition Methods= 0
Advection Scheme= 1
Matrix Solver= 0
Implicit Weighting Factor= 1
Maximum Outer Loop Convergence Iterations= 5
Convergence Maximum Absolute= 0.001
Convergence RMSE= 0.0001
Grain Fractions Max Abs Error= 0.001
Max Subgrid Regions= 1
Max Subgrid Length Scale= 3.402823E+38
Initial Layer Thickness= 3.402823E+38
Min Layer Thickness= 3.402823E+38
Max Layer Thickness= 3.402823E+38
Number of Layers= 5

--- LTTLLAURLCK.f01 (steady flow) ---

Flow Title=Flow
Program Version=6.00
Number of Profiles= 6
Profile Names=01pct,10pct,04pct,02pct,0_2pct,01plus
River Rch & RM=LTTLLAURLCK,Main,9154
     590     312     415     499     823     872
River Rch & RM=LTTLLAURLCK,Main,6297
     691     368     488     586     962    1020
River Rch & RM=LTTLLAURLCK,Main,4663
     962     518     683     818    1330    1420
Boundary for River Rch & Prof#=LTTLLAURLCK,Main            , 1
Up Type= 0
Dn Type= 3
Dn Slope=0.00721
Boundary for River Rch & Prof#=LTTLLAURLCK,Main            , 2
Up Type= 0
Dn Type= 3
Dn Slope=0.00721
Boundary for River Rch & Prof#=LTTLLAURLCK,Main            , 3
Up Type= 0
Dn Type= 3
Dn Slope=0.00721
Boundary for River Rch & Prof#=LTTLLAURLCK,Main            , 4
Up Type= 0
Dn Type= 3
Dn Slope=0.00721
Boundary for River Rch & Prof#=LTTLLAURLCK,Main            , 5
Up Type= 0
Dn Type= 3
Dn Slope=0.00721
Boundary for River Rch & Prof#=LTTLLAURLCK,Main            , 6
Up Type= 0
Dn Type= 3
Dn Slope=0.00721
DSS Import GetInterval= 0
DSS Import GetPeak= 0
DSS Import FillOption= 0

--- LTTLLAURLCK.g01 (geometry) ---

Geom Title=Geometry
Program Version=6.10

River Reach=LTTLLAURLCK     ,Main
Reach XY= 30
2202037.32500003484536.5030000062201780.27100001484317.886999995
2201311.92200001484297.1770000162201229.64500003484311.161000013
2201108.84199999484481.6930000042200834.16500001484527.161000013
2200150.36905102484103.8418422942199672.20599999484096.430000022
2199256.14452888483582.202582255     2199192.895483355.489999995
2199239.43650003483285.1325000082199076.61927085483111.701894209
2198929.62856092482667.3217259352198741.49683495482468.472722903
2198516.74100004482355.4410000152198367.35000007482112.621000037
2198230.22151946482106.8463330722198236.90500002481955.531000018
2198157.27500002 481829.510000022198217.74100004481789.582000002
2197955.12900002481692.9885000142197943.56664045481407.513283893
2197447.36644383 481187.461571412197305.26491778480879.811370835
2197093.06199999480972.9239999952197005.98600005480737.859000027
2196945.53200002481033.6990000162196793.25000001481142.431000024
2196814.17000003481277.1439999792196403.44371806481155.615178749

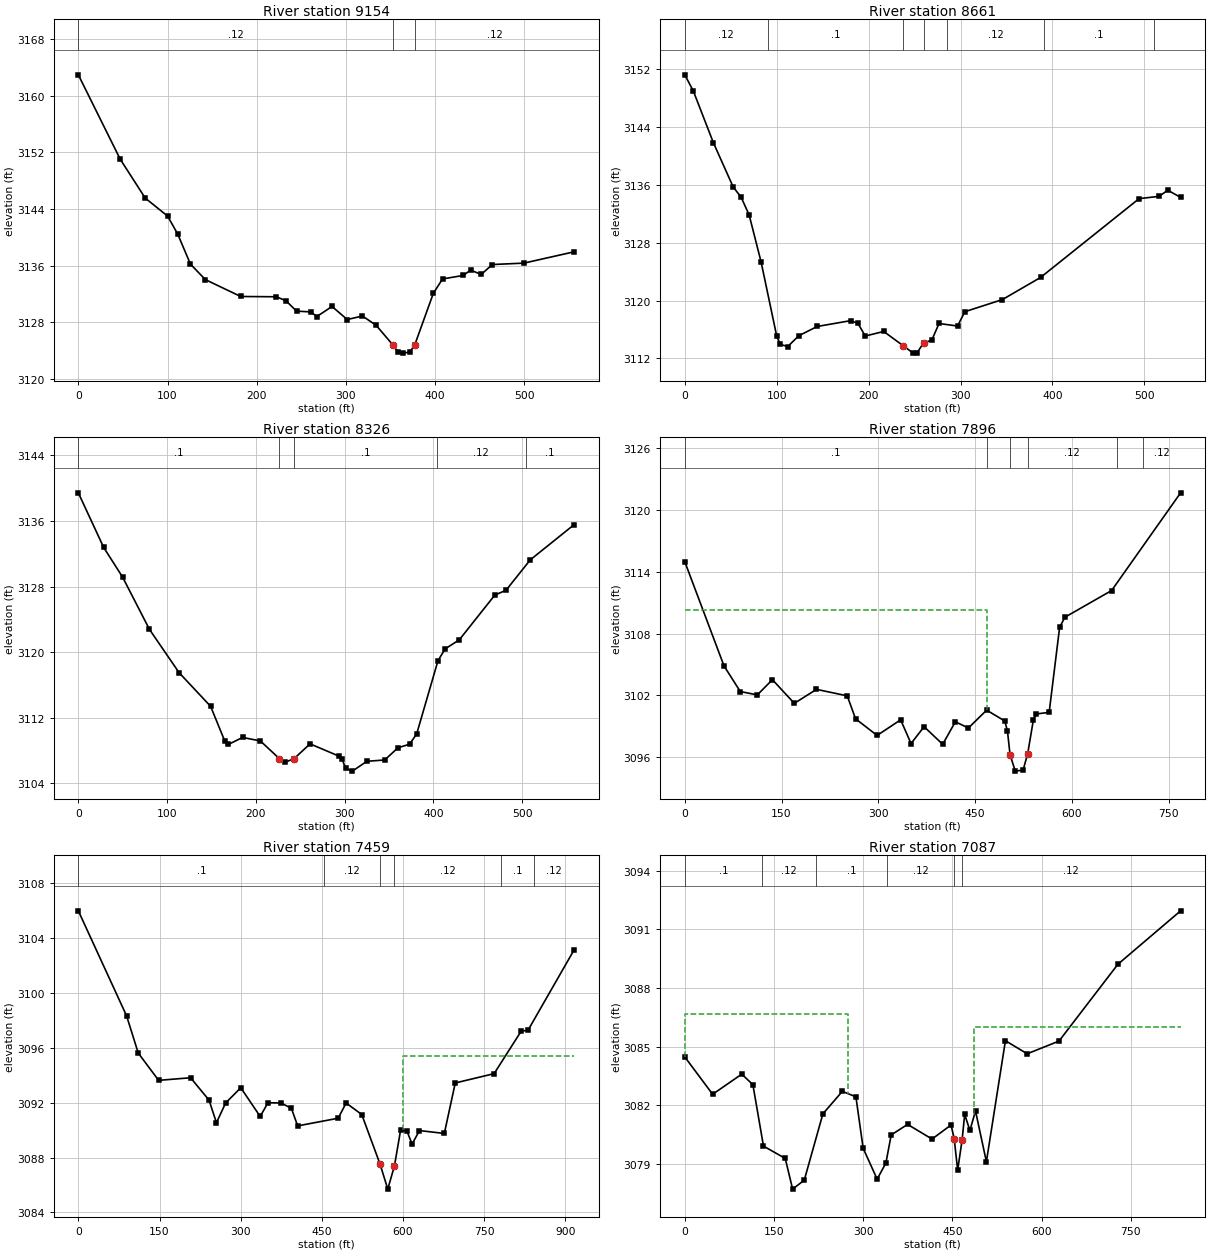
Type RM Length L Ch R = 1 ,9154    ,507.5,493.7,478.9
XS GIS Cut Line= 3
2202281.46838244484268.9673717462201985.15760548484562.521320167
2201983.67385269484701.395153349
#Sta/Elev= 30
       0 3162.97    46.9 3151.05      75 3145.54   100.1 3142.99   111.4 3140.46
   125.7  3136.2   142.4 3134.01   182.1 3131.62     222 3131.58   232.7 3131.03
   244.7 3129.55   260.8 3129.44   267.4 3128.78   284.5 3130.21   301.5 3128.36
   318.6 3128.86     334 3127.54   352.7 3124.77   358.4 3123.77     364 3123.61
   371.6 3123.76   377.2 3124.76   398.1 3132.07   408.4  3134.1   431.8  3134.6
   439.8 3135.35   451.8 3134.74   464.2 3136.14   499.7 3136.34     556 3137.94
#Mann= 3 ,-1,0
       0     .12       0   352.7    .045       0   377.2     .12       0
Bank Sta=352.7,377.2
XS Rating Curve= 0 ,0
Exp/Cntr=0.3,0.1

Type RM Length L Ch R = 1 ,8661    ,332.2,334.4,335.7
XS GIS Cut Line= 4
2201635.22188011484088.5931668182201598.51983337 484176.57417338
 2201619.7363303484420.9924944412201718.67318355 484593.38400465
#Sta/Elev= 30
       0 3151.15     9.3 3148.91      31 3141.81    52.6 3135.68    61.3 3134.25
      70 3131.81      83 3125.32     100 3115.08     104 3113.94     112 3113.65
     124 3115.14   144.1 3116.42   180.3 3117.22   188.3 3116.86   196.3  3115.1
   216.4 3115.73   237.8 3113.74   248.5 3112.74   252.6 3112.79     260 3114.18
   268.6 3114.51   276.6 3116.83   296.7 3116.48   304.7 3118.46   345.5 3120.13
     387 3123.18   494.2 3134.06   516.1 3134.38   525.4 3135.23   539.4 3134.23
#Mann= 7 ,-1,0
       0     .12       0      90      .1       0   237.8    .045       0
     260      .1       0  285.33     .12       0  390.67      .1       0
  510.67     .12       0
Bank Sta=237.8,260
XS Rating Curve= 0 ,0
Exp/Cntr=0.3,0.1

Type RM Length L Ch R = 1 ,8326    ,429.4,430.2,432.8
XS GIS Cut Line= 3
2201348.81493912484072.2847434922201291.14970605484203.963590665
2201303.04969656484618.493810412
#Sta/Elev= 30
       0 3139.44    28.5 3132.78    49.8 3129.16    80.1 3122.77   113.5 3117.48
     149 3113.37     165 3109.12     169 3108.72     185 3109.57     205 3109.15
   226.3    3107     233 3106.54   243.2    3107     261 3108.79   293.8 3107.28
     297 3106.98     301 3105.79   308.7 3105.46     325 3106.66   345.1 3106.82
   359.9  3108.3   373.1 3108.75   381.1    3110   405.1 3118.94   413.1 3120.38
   429.1 3121.49   469.1 3126.95   481.8 3127.55   509.1 3131.26   558.5 3135.56
#Mann= 5 ,-1,0
       0      .1       0   226.3    .045       0   243.2      .1       0
  403.75     .12       0  503.75      .1       0
Bank Sta=226.3,243.2
XS Rating Curve= 0 ,0
Exp/Cntr=0.3,0.1

Type RM Length L Ch R = 1 ,7896    ,423.3,437.1,450.3
XS GIS Cut Line= 4
2201146.60147821484087.5475846722200938.59361437484301.096959425
2200980.73631015484599.5885070152201066.17607574484745.391505033
#Sta/Elev= 30
       0 3114.98    60.8 3104.85      86 3102.36   112.4 3102.03   135.8 3103.51
   169.8 3101.21   204.1 3102.57   251.8 3101.94   264.7 3099.71   298.1 3098.09
   334.6 3099.61   350.7  3097.3   370.9 3098.94   399.8 3097.23   419.4 3099.42
   439.6 3098.81   467.9 3100.55   496.1 3099.49   500.2  3098.5   504.2  3096.2
   512.3 3094.62   524.4 3094.72   531.5 3096.31   540.3 3099.58   544.6 3100.18
   564.8 3100.33     581 3108.59   589.1 3109.58   661.6 3112.18   768.6 3121.68
#Mann= 6 ,-1,0
       0      .1       0  468.11     .12       0   504.2    .045       0
   531.5     .12       0  669.56      .1       0  709.56     .12       0
#XS Ineff= 2 , 0
          468.41  3110.3
Permanent Ineff=
       F       F
Bank Sta=504.2,531.5
XS Rating Curve= 0 ,0
Exp/Cntr(USF)=0,0
Exp/Cntr=0.3,0.1

Type RM Length L Ch R = 1 ,7459    ,370.6,371.8,369.1
XS GIS Cut Line= 4
2200942.42146537483950.3587350362200738.33096473484134.211418058
 2200501.2583987484488.8205904592200562.15802881484694.987113386
#Sta/Elev= 30
       0 3105.99    89.2 3098.33   110.7 3095.62   148.4 3093.63   207.4 3093.82
   241.5 3092.19   255.2 3090.54   272.2 3091.98   300.2 3093.09     336    3091
   350.5    3092   374.5 3091.98   393.7 3091.59   405.3 3090.31   480.2 3090.87
   494.8 3091.98   523.7 3091.14   557.63087.514   571.8  3085.7   584.1 3087.39
   595.6 3090.02   607.1 3089.94   616.8 3088.98   630.2 3089.97   676.3 3089.76
   696.5 3093.44   768.3 3094.12   818.4 3097.22   830.9 3097.28   916.2 3103.15
#Mann= 6 ,-1,0
       0      .1       0  454.69     .12       0   557.6    .045       0
   584.1     .12       0  781.25      .1       0  841.25     .12       0
#XS Ineff= 2 , 0
                          599.03         3095.44
Permanent Ineff=
       F       F
Bank Sta=557.6,584.1
XS Rating Curve= 0 ,0
Exp/Cntr=0.3,0.1

Type RM Length L Ch R = 1 ,7087    ,370.3,367.6,361.2
XS GIS Cut Line= 3
2200503.88551441483785.3487829922200209.07520493484318.723572024
2200289.55372072484528.057405206
#Sta/Elev= 30
       0 3084.47    46.8 3082.56    95.8 3083.59   114.5 3083.05   132.3 3079.91
   168.9 3079.28   181.3 3077.71   200.9 3078.17   232.2 3081.56   264.9 3082.71
   287.7 3082.43   299.9  3079.8   323.4 3078.22   338.2 3079.05     347 3080.48
   374.6 3081.02   415.7 3080.27   447.7 3080.99     453 3080.28   458.8 3078.68
   466.33080.229   470.6 3081.53   479.4 3080.71   488.8 3081.71   507.1 3079.11
   539.1  3085.3   575.7 3084.63   629.2 3085.28   728.3 3089.21   833.7 3091.94
#Mann= 6 ,-1,0
       0      .1       0     130     .12       0     220      .1       0
     340     .12       0     453    .045       0   466.3     .12       0
#XS Ineff= 2 , 0
           274.4 3086.68  486.96         3086.02
Permanent Ineff=
       F       F
Bank Sta=453,466.3
XS Rating Curve= 0 ,0
Exp/Cntr=0.3,0.1

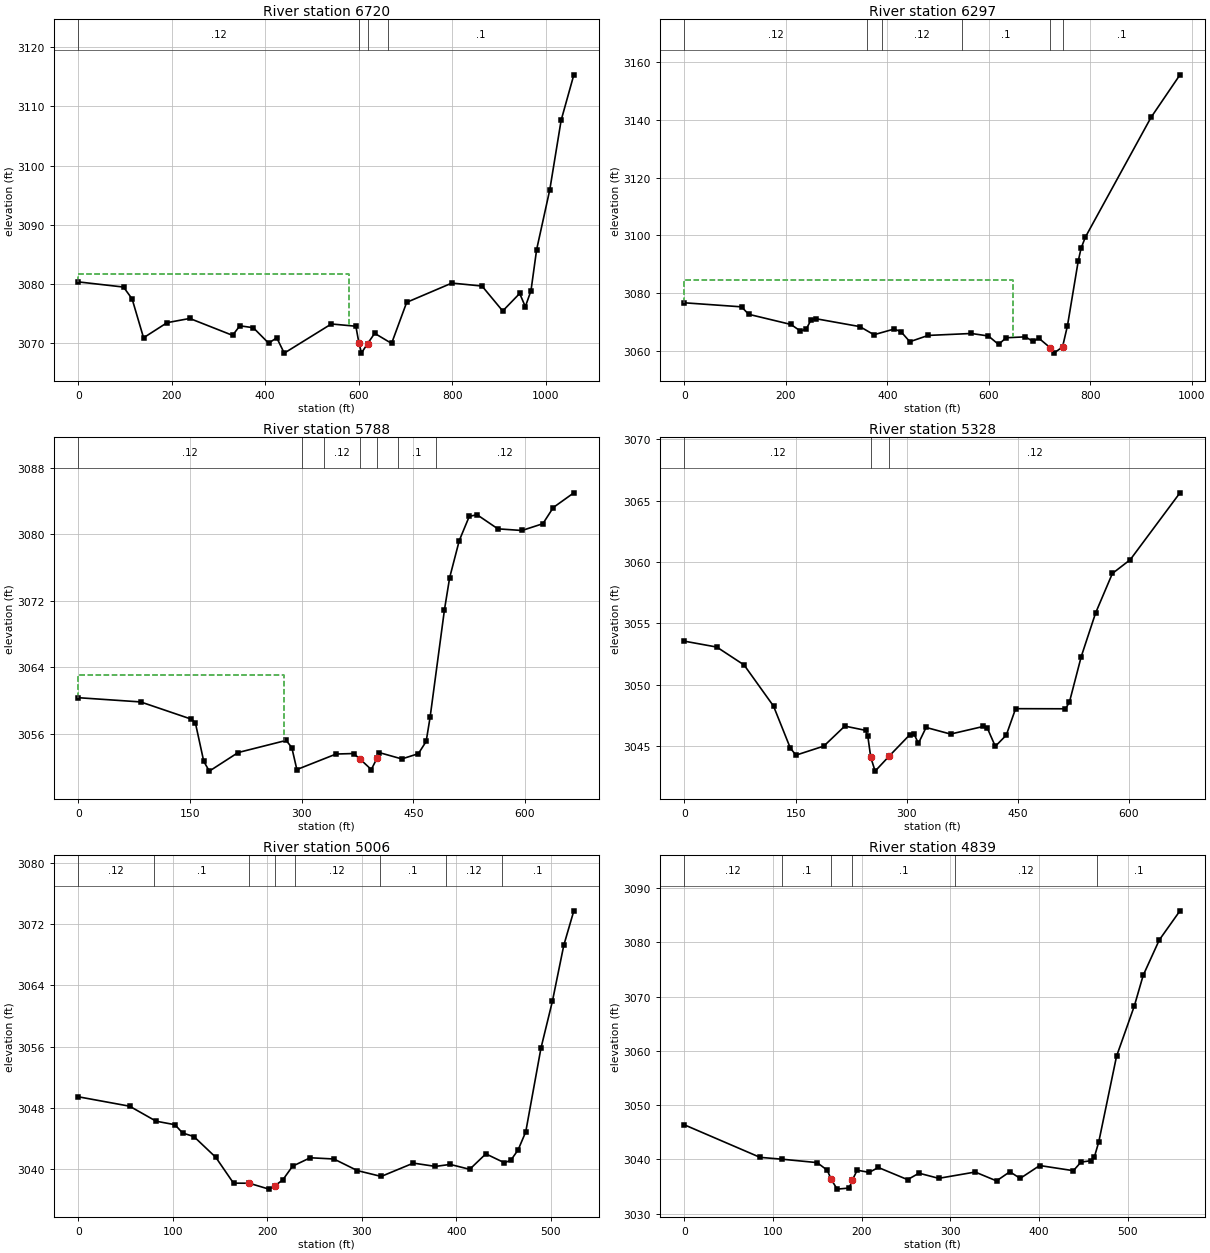
Type RM Length L Ch R = 1 ,6720    ,411.3,422.6,433.7
XS GIS Cut Line= 3
2200329.85216817483647.0935002532199979.07177636483883.743977076
2199900.92257282484516.239612019
#Sta/Elev= 30
       0 3080.38    96.7 3079.51   115.1 3077.51   139.6 3070.95     190  3073.5
   238.5 3074.21   330.1 3071.36   345.6 3072.97   374.4 3072.65   407.3 3070.04
   424.6 3070.95   440.7 3068.36   541.5 3073.28   593.9  3072.9   600.63070.036
     606  3068.4   619.2 3069.98   634.2  3071.7   670.4    3070   702.7 3076.93
   799.4 3080.18   863.9 3079.68   908.2 3075.47   944.5 3078.43   956.6 3076.19
   968.7  3078.9   980.8 3085.84    1009 3095.96  1033.2 3107.64  1060.4 3115.32
#Mann= 4 ,-1,0
       0     .12       0   600.6    .045       0   619.2     .12       0
  663.14      .1       0
#XS Ineff= 2 , 0
          579.63 3081.68
Permanent Ineff=
       F       F
Bank Sta=600.6,619.2
XS Rating Curve= 0 ,0
Exp/Cntr=0.3,0.1

Type RM Length L Ch R = 1 ,6297    ,507.2,509,510.1
XS GIS Cut Line= 3
2200202.01487955483622.592765883 2199770.2779098483826.604493516
2199419.07633165484181.801782873
#Sta/Elev= 30
       0 3076.71   112.6 3075.31   126.5 3072.74     210 3069.22   228.7 3066.94
   240.1 3067.62   249.7 3070.82   258.6 3071.22   345.8 3068.48   373.7 3065.67
   413.5 3067.64   426.9 3066.73   444.4 3063.26   480.5 3065.43   565.7  3066.1
   599.3 3065.24   619.4  3062.3   634.1 3064.62   672.4 3064.94   687.3 3063.33
   698.6 3064.49   721.2 3061.16   728.6 3059.31   745.5 3061.47   755.2  3068.8
   776.3 3091.04     782 3095.55   790.5 3099.41   919.9 3140.79     977 3155.52
#Mann= 6 ,-1,0
       0     .12       0     360      .1       0     390     .12       0
  547.51      .1       0   721.2    .045       0   745.5      .1       0
#XS Ineff= 2 , 0
          647.34 3084.56
Permanent Ineff=
       F       F
Bank Sta=721.2,745.5
XS Rating Curve= 0 ,0
Exp/Cntr=0.3,0.1

Type RM Length L Ch R = 1 ,5788    ,458.9,460.4,457.3
XS GIS Cut Line= 3
2199583.39910279483366.8091112682199171.32170408483719.004483672
2199107.40425074 483824.83007858
#Sta/Elev= 30
       0 3060.33    83.7 3059.82   151.6 3057.75   157.2 3057.33   168.5 3052.66
     176 3051.48   214.7 3053.72   279.2 3055.18   286.8 3054.32   293.6 3051.67
   346.3 3053.54   369.8  3053.6   378.5 3052.93   393.6 3051.67   401.2 3053.03
   404.1 3053.72   434.6 3052.95   456.8 3053.58   467.3 3055.06   472.6 3057.97
   491.9 3070.94   498.9 3074.81   511.8 3079.27   525.2 3082.18   535.7 3082.38
   563.6 3080.68     596 3080.48   624.1  3081.3   638.1 3083.25   665.7 3085.02
#Mann= 7 ,-1,0
       0     .12       0     300      .1       0     330     .12       0
   378.5    .045       0   401.2     .12       0     430      .1       0
     480     .12       0
#XS Ineff= 2 , 0
           276.1 3063.06
Permanent Ineff=
       F       F
Bank Sta=378.5,401.2
XS Rating Curve= 0 ,0
Exp/Cntr(USF)=0,0
Exp/Cntr=0.3,0.1

Type RM Length L Ch R = 1 ,5328    ,317.2,322.2,320.6
XS GIS Cut Line= 3
2199385.77278849483040.9381601732199008.18205636483395.986162025
 2199049.5103952483540.635347965
#Sta/Elev= 30
       0 3053.54    43.7 3053.06    80.5  3051.6   120.2 3048.25   142.8 3044.84
   150.4 3044.25   188.1 3044.99   216.4 3046.62   244.7 3046.27   247.5 3045.78
   251.4 3044.08   257.3 3042.95   276.7  3044.2     304 3045.91   309.7    3046
   315.7 3045.21   326.1 3046.51   359.1 3045.97   403.3 3046.59   408.5 3046.49
   419.5 3044.97   434.3 3045.88   446.9 3048.04   514.2 3048.03   519.5 3048.57
   535.4 3052.27   554.8 3055.83   577.5 3059.06   601.6 3060.18   668.7 3065.63
#Mann= 3 ,-1,0
       0     .12       0   251.4    .045       0   276.7     .12       0
Bank Sta=251.4,276.7
XS Rating Curve= 0 ,0
Exp/Cntr(USF)=0,0
Exp/Cntr=0.3,0.1

Type RM Length L Ch R = 1 ,5006    ,161.4,166.4,168.6
XS GIS Cut Line= 4
2199242.47151934482930.7056323392199103.73909609482928.843452161
2198856.06913244483135.5454519042198793.68609648483143.925262705
#Sta/Elev= 30
       0 3049.45    54.3 3048.22    82.3 3046.26   102.3  3045.8   110.3 3044.72
   122.3 3044.25   145.5 3041.53   164.2 3038.16   180.83038.151   201.7 3037.38
   207.9 3037.82   216.3 3038.58   226.7 3040.38   245.4 3041.48   270.4 3041.32
   295.3  3039.8   320.5 3039.04   354.5 3040.78   377.8 3040.35   393.5 3040.61
   414.1 3039.97   431.2 3041.99   450.8 3040.83   457.6 3041.15   465.3  3042.5
   473.4 3044.86   489.5  3055.8   501.6 3061.93   513.7 3069.27   524.3 3073.76
#Mann= 8 ,-1,0
       0     .12       0      80      .1       0   180.8    .045       0
   207.9      .1       0  228.74     .12       0  318.74      .1       0
  388.74     .12       0  448.74      .1       0
Bank Sta=180.8,207.9
XS Rating Curve= 0 ,0
Exp/Cntr(USF)=0,0
Exp/Cntr=0.3,0.1

Type RM Length L Ch R = 1 ,4839    ,175.9,176,176.1
XS GIS Cut Line= 4
2199161.89101548482850.868177401 2199038.8197365 482800.10127482
2198957.28501417482843.1762224652198691.14337337483044.705441801
#Sta/Elev= 30
       0 3046.35    85.3 3040.36     110 3040.02   149.7 3039.39   161.1    3038
   165.7 3036.28   172.3  3034.5   185.9  3034.7   189.53036.165   194.9 3037.99
   208.5 3037.59   218.8 3038.49   251.8 3036.25   264.7 3037.44   286.9 3036.49
   328.1 3037.65   352.2 3036.02   367.2  3037.7   378.9 3036.48   400.9 3038.85
   438.9  3037.9   447.5 3039.48   458.8 3039.74   462.6 3040.42   467.6 3043.23
   487.6 3058.98   507.7 3068.27   517.7 3073.92   535.9 3080.45   559.2 3085.81
#Mann= 6 ,-1,0
       0     .12       0     110      .1       0   165.7    .045       0
   189.5      .1       0  305.34     .12       0  465.34      .1       0
Bank Sta=165.7,189.5
XS Rating Curve= 0 ,0
Exp/Cntr(USF)=0,0
Exp/Cntr=0.3,0.1

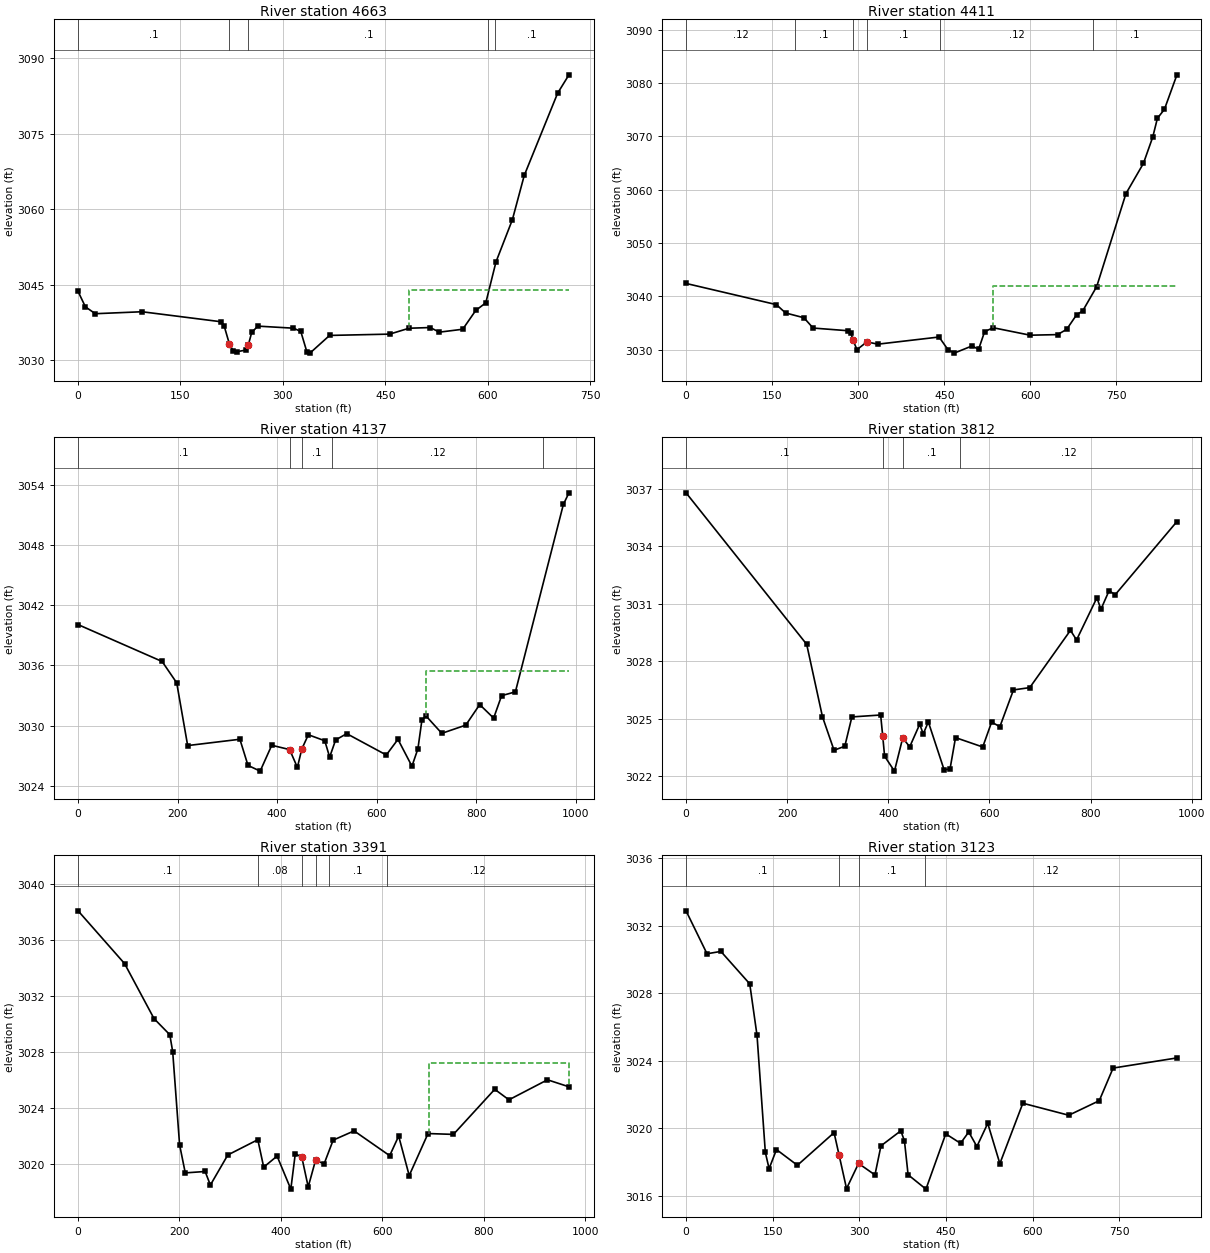
Type RM Length L Ch R = 1 ,4663    ,259.4,251.9,245.5
XS GIS Cut Line= 4
2199124.96963178482530.8828520432198966.51536009482641.647003129
2198737.29510299482758.5647181632198620.37738795483000.092103169
#Sta/Elev= 30
       0 3043.63    10.7 3040.58    25.2 3039.21    93.7  3039.6   209.4 3037.61
   213.9  3036.8   221.5 3033.25   227.4 3031.75   233.4 3031.67   245.4 3031.97
   249.53033.069   254.3 3035.49   263.3 3036.74   315.5 3036.33   326.2 3035.68
   335.2 3031.58   339.6 3031.37   368.4 3034.89   456.4 3035.15   484.7 3036.32
   515.8 3036.46   529.1 3035.54   563.4 3036.12   582.4 3039.85   597.2 3041.38
   612.1 3049.51   636.1  3057.9   653.5 3066.71   702.4 3083.07     719 3086.72
#Mann= 5 ,-1,0
       0      .1       0   221.5    .045       0   249.5      .1       0
  600.65     .12       0  610.65      .1       0
#XS Ineff= 2 , 0
                          485.39         3043.97
Permanent Ineff=
       F       F
Bank Sta=221.5,249.5
XS Rating Curve= 0 ,0
Exp/Cntr(USF)=0,0
Exp/Cntr=0.3,0.1

Type RM Length L Ch R = 1 ,4411    ,271,273.8,274.9
XS GIS Cut Line= 4
2199049.58847341482450.8865207032198786.52361458482450.886520703
2198514.22840983482764.7182821132198481.92219909482938.556463677
#Sta/Elev= 30
       0 3042.41   157.4 3038.44   173.4 3036.88   205.4 3035.98   221.4 3034.05
     282 3033.55   287.3 3033.12   291.1 3031.72   297.9 3030.01   315.13031.451
   334.4 3031.03   440.9 3032.37   456.3 3030.02   467.3 3029.35   498.6 3030.71
   509.7 3030.04   520.3 3033.38   535.2 3034.11   599.7 3032.71   647.4 3032.82
   663.3 3033.81   680.7 3036.56   691.2 3037.26   715.6 3041.82   766.5 3059.23
     797 3064.91   813.3 3069.86   821.4 3073.37   833.6 3075.04   855.4 3081.51
#Mann= 6 ,-1,0
       0     .12       0     190      .1       0   291.1    .045       0
   315.1      .1       0  443.06     .12       0  708.56      .1       0
#XS Ineff= 2 , 0
                           535.3         3041.97
Permanent Ineff=
       F       F
Bank Sta=291.1,315.1
XS Rating Curve= 0 ,0
Exp/Cntr(USF)=0,0
Exp/Cntr=0.3,0.1

Type RM Length L Ch R = 1 ,4137    ,320.7,325.1,323
XS GIS Cut Line= 4
2198886.95858875482153.5277950722198709.95352841482180.886282202
2198386.60569052482487.046669143 2198400.6389105482848.330667901
#Sta/Elev= 30
       0 3040.07   168.8 3036.39   198.1 3034.26   220.1    3028     325 3028.63
   341.3 3026.02   365.7 3025.45     389 3028.03   424.9  3027.6   440.5 3025.82
   449.4 3027.66   462.5 3029.08   495.5 3028.48   505.3 3026.85   517.3 3028.56
   539.6 3029.19   619.1 3027.06   642.5 3028.62   670.6 3025.94   682.6 3027.68
   690.6 3030.53   698.6 3030.97   730.6 3029.22   778.7 3030.04   806.7 3032.09
   834.7 3030.74   850.7 3032.98   878.4 3033.36   974.8 3052.07     986 3053.22
#Mann= 5 ,-1,0
       0      .1       0   424.9    .045       0   449.4      .1       0
  509.11     .12       0   934.4      .1       0
#XS Ineff= 2 , 0
                          698.66         3035.43
Permanent Ineff=
       F       F
Bank Sta=424.9,449.4
XS Rating Curve= 0 ,0
Exp/Cntr=0.3,0.1

Type RM Length L Ch R = 1 ,3812    ,402.3,421,415.7
XS GIS Cut Line= 4
2198728.40646472481962.3725425942198525.69096271481968.064581988
2198214.99991551482256.2399501882198177.62311519482598.518176728
#Sta/Elev= 30
       0  3036.8   238.6 3028.89   269.8 3025.11   292.7 3023.36     314 3023.57
     328  3025.1   384.9  3025.2   388.93024.124   392.7 3023.05   412.2 3022.27
   428.5    3024   442.4 3023.54   462.2 3024.72   469.1 3024.21   479.2 3024.84
   510.4 3022.34   522.1 3022.38     533 3024.02   586.8 3023.53   604.4 3024.83
   620.7 3024.59   647.6 3026.51   679.8 3026.63   760.3 3029.62   772.4 3029.12
   812.6 3031.32   820.6 3030.72   836.7 3031.69   848.8 3031.48   970.9  3035.3
#Mann= 4 ,-1,0
       0      .1       0   388.9    .045       0   428.5      .1       0
   542.8     .12       0
Bank Sta=388.9,428.5
XS Rating Curve= 0 ,0
Exp/Cntr(USF)=0,0
Exp/Cntr=0.3,0.1

Type RM Length L Ch R = 1 ,3391    ,248.5,268.5,264.7
XS GIS Cut Line= 5
 2198518.7572351  481566.14535432198326.56768652481762.365492419
2198127.66693422481979.2134054572197998.31766116482091.708785847
2197996.92931666482319.614036847
#Sta/Elev= 30
       0 3038.06    91.7 3034.29   149.8 3030.36   180.9 3029.21   186.6    3028
   200.2 3021.35   211.4 3019.34   250.6 3019.44   260.9 3018.47   295.3 3020.62
   354.5 3021.71   366.1 3019.75   392.5 3020.54   419.6 3018.18   428.4 3020.71
   441.3 3020.46   453.9 3018.34   468.33020.234   485.3 3019.99   503.1 3021.68
   544.4 3022.34   614.6 3020.57   632.3 3021.97   653.1 3019.15   690.2 3022.15
   740.3 3022.09   821.8 3025.31   849.8 3024.56   925.8 3025.99   968.2 3025.49
#Mann= 6 ,-1,0
       0      .1       0  354.66     .08       0   441.3    .045       0
   468.3     .08       0  494.66      .1       0  608.91     .12       0
#XS Ineff= 2 , 0
                          692.75          3027.2
Permanent Ineff=
       F       F
Bank Sta=441.3,468.3
XS Rating Curve= 0 ,0
Exp/Cntr=0.3,0.1

Type RM Length L Ch R = 1 ,3123    ,212.9,213.2,214
XS GIS Cut Line= 4
2198394.32137202 481575.813102122198166.98137057481727.942877531
2197943.06001575481998.0159619682197944.76933907482223.646640105
#Sta/Elev= 30
       0 3032.87    36.3 3030.33    60.3 3030.47   110.3 3028.55   122.9  3025.5
   137.3 3018.58   143.8 3017.62   156.6 3018.75   192.8 3017.82   256.3 3019.75
   264.9 3018.44   277.9 3016.44   298.73017.929   327.1 3017.25   337.5 3018.97
   371.9 3019.86   378.2 3019.26   384.5 3017.26   415.4 3016.41   449.7 3019.68
   475.3 3019.12   489.5 3019.79   503.6 3018.93   522.4  3020.3   543.4 3017.92
   583.2 3021.49   662.7 3020.78   715.5 3021.64   739.5 3023.57     850 3024.17
#Mann= 4 ,-1,0
       0      .1       0   264.9    .045       0   298.7      .1       0
  413.55     .12       0
Bank Sta=264.9,298.7
XS Rating Curve= 0 ,0
Exp/Cntr(USF)=0,0
Exp/Cntr=0.3,0.1

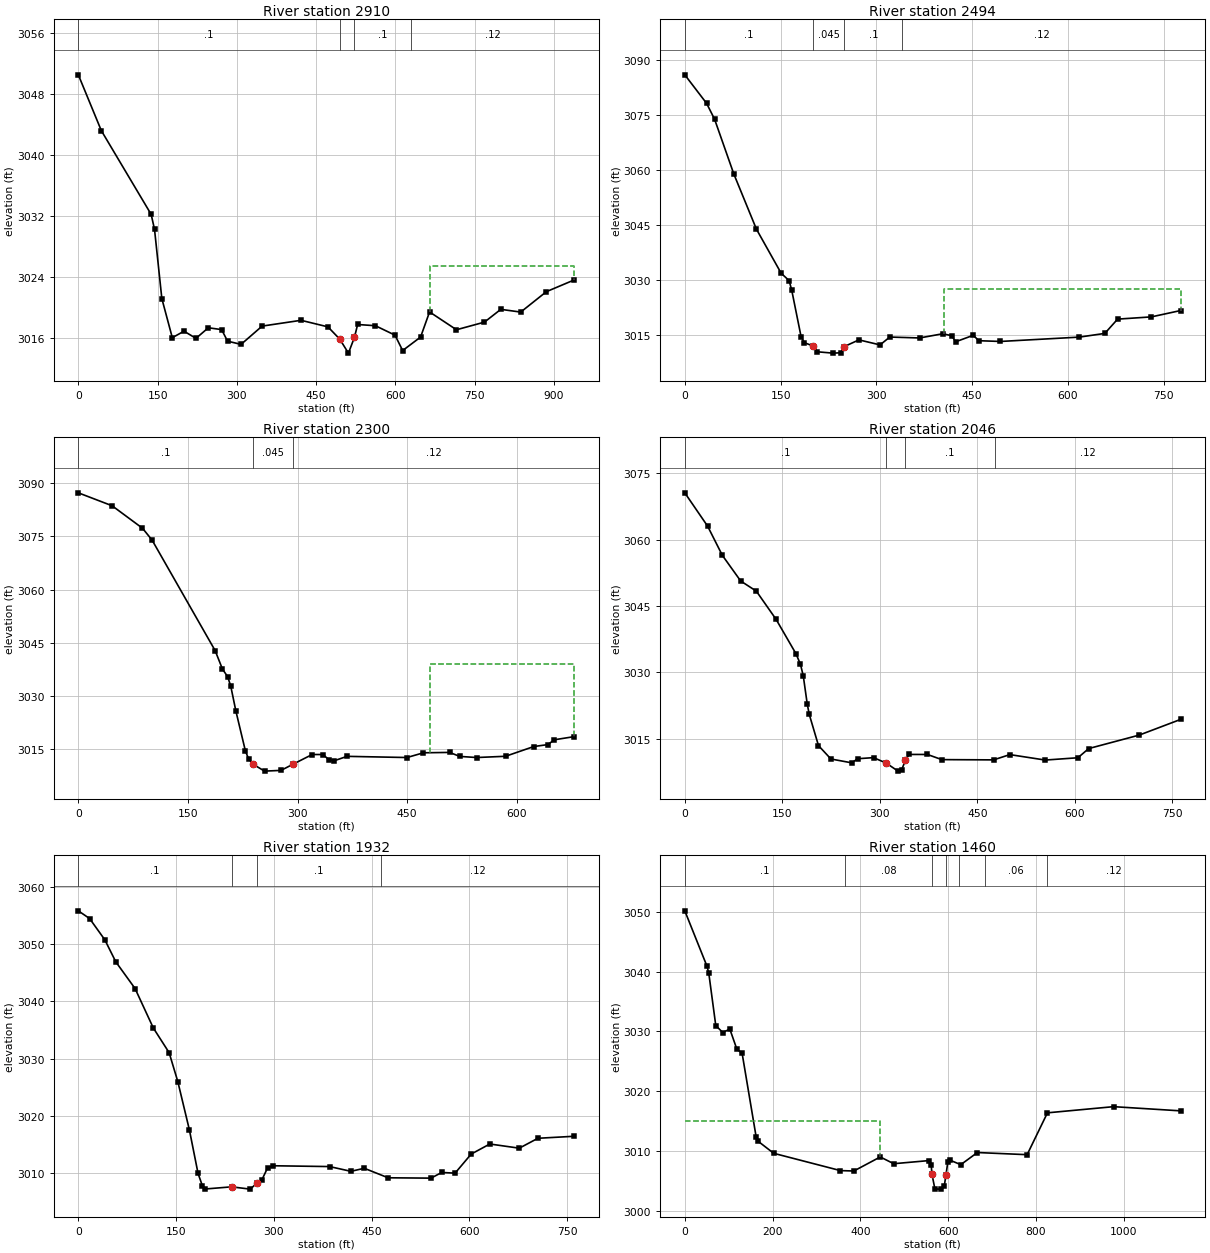
Type RM Length L Ch R = 1 ,2910    ,414.9,415.5,394.8
XS GIS Cut Line= 4
2198274.66873968481310.8679876412198249.02888989481416.846033433
2197808.02347353481857.8514497922197837.08196996482061.260924779
#Sta/Elev= 30
       0  3050.5    43.5 3043.17   137.8 3032.17   144.2 3030.19     158 3021.12
   177.8 3015.98     200 3016.83   222.6 3015.89     246 3017.28   271.1 3017.04
   282.4 3015.52   307.9  3015.1   347.8  3017.5   421.4 3018.26   472.3  3017.4
   494.5  3015.8   511.1 3013.95   522.5 3016.03   528.5 3017.71   562.1 3017.55
   599.2 3016.31   613.7 3014.29   647.6 3016.06   664.6 3019.36   715.5 3017.02
   768.4 3018.02   799.4  3019.7   837.1 3019.34   885.6 3022.02   938.2 3023.56
#Mann= 4 ,-1,0
       0      .1       0   494.5    .045       0   522.5      .1       0
  629.04     .12       0
#XS Ineff= 2 , 0
                          666.14         3025.38
Permanent Ineff=
       F       F
Bank Sta=494.5,522.5
XS Rating Curve= 0 ,0
Exp/Cntr(USF)=0,0
Exp/Cntr=0.3,0.1

Type RM Length L Ch R = 1 ,2494    ,200.5,194.2,183.8
XS GIS Cut Line= 4
2197934.51339915 481160.447535552197886.65234621481324.542574195
2197655.89369812481608.2902451862197640.50978824481847.595509877
#Sta/Elev= 30
       0 3085.87    34.1 3078.11    46.6  3073.8    76.7  3058.9   112.2 3043.83
   150.9 3031.84   163.3 3029.83   167.4 3027.27   182.1 3014.57   187.2 3012.92
   200.2 3012.08   207.8 3010.44   231.9 3010.08   244.2 3010.17   249.9 3011.88
   272.7 3013.69   305.8 3012.32     321 3014.46   367.7 3014.21   403.8 3015.35
   417.7 3014.85   424.4 3013.18   451.8 3014.94   460.5 3013.46   494.4 3013.26
   617.7 3014.44   657.8 3015.45   677.8 3019.34   730.7 3019.95   776.5 3021.68
#Mann= 4 ,-1,0
       0      .1       0   200.2    .045       0   249.9      .1       0
  340.93     .12       0
#XS Ineff= 2 , 0
                          405.42         3027.59
Permanent Ineff=
       F       F
Bank Sta=200.2,249.9
XS Rating Curve= 0 ,0
Exp/Cntr(USF)=0,0
Exp/Cntr=0.3,0.1

Type RM Length L Ch R = 1 ,2300    ,245.4,253.4,255.2
XS GIS Cut Line= 4
2197874.68708298481107.4585126542197705.46407437481223.692498361
2197657.60302144 481334.798514112197461.03083973481627.092801697
#Sta/Elev= 30
       0 3087.24    46.2  3083.6    87.8 3077.27   100.9 3073.94   187.2 3042.82
   197.2 3037.62   204.4 3035.45   208.6 3032.78   215.6 3025.79   228.6 3014.58
     233 3012.33   239.43010.785   254.8 3008.88   277.4 3009.09     294 3010.85
     320 3013.56   334.8 3013.55   343.4    3012   350.3 3011.81   367.7 3013.04
   449.7 3012.71   472.2 3014.04     508 3014.15     522 3013.02   545.2 3012.71
   584.6 3013.06   623.2  3015.8   642.5 3016.35   651.4 3017.71   678.5 3018.59
#Mann= 3 ,-1,0
       0      .1       0   239.4    .045       0     294     .12       0
#XS Ineff= 2 , 0
                          481.55         3039.08
Permanent Ineff=
       F       F
Bank Sta=239.4,294
XS Rating Curve= 0 ,0
Exp/Cntr(USF)=0,0
Exp/Cntr=0.3,0.1

Type RM Length L Ch R = 1 ,2046    ,102.4,114.9,119.7
XS GIS Cut Line= 5
2197672.98693131480943.3634740092197543.07835905481073.272046269
2197421.71640338481223.6924983612197341.37820738481485.218966202
2197355.05279393481596.324981951
#Sta/Elev= 30
       0 3070.57    35.1 3063.04    57.7 3056.46      86 3050.65     110 3048.37
   140.5 3041.97   170.9 3034.25   177.9 3031.83   182.2 3029.23   188.3 3022.87
   191.4 3020.53   205.6 3013.48   224.7 3010.46   256.8 3009.59   265.8 3010.52
   290.3 3010.77   309.9 3009.52   327.9 3007.72   333.6 3008.07   339.3 3010.15
     345 3011.49   373.1 3011.48   395.3 3010.32   474.8 3010.26   499.9 3011.45
   554.3 3010.22   604.5 3010.74   621.2 3012.82   698.9 3015.86   762.5  3019.4
#Mann= 4 ,-1,0
       0      .1       0   309.9    .045       0   339.3      .1       0
  476.99     .12       0
Bank Sta=309.9,339.3
XS Rating Curve= 0 ,0
Exp/Cntr(USF)=0,0
Exp/Cntr=0.3,0.1

Type RM Length L Ch R = 1 ,1932    ,488.6,471.6,454.6
XS GIS Cut Line= 4
2197584.10211871480914.3049775822197514.01986262481032.248286608
2197291.80783112481139.935655719 2197209.7603118481507.440169352
#Sta/Elev= 30
       0 3055.83    17.3 3054.48    40.6 3050.78    57.5 3046.92    87.1 3042.25
     115 3035.38   139.3 3031.06   152.6 3026.02   170.4 3017.57   183.7 3009.96
   190.2 3007.86   194.4 3007.25   235.1 3007.63   263.7 3007.23     274 3008.28
   281.5 3008.83   290.4 3010.95   299.3 3011.31   385.4 3011.17   418.2 3010.34
   438.7 3010.87   475.3 3009.21   541.1 3009.15   557.5 3010.14     578 3010.02
   602.7 3013.35   631.3 3015.11   676.5 3014.38   705.1 3016.11   760.7 3016.46
#Mann= 4 ,-1,0
       0      .1       0   235.1    .045       0     274      .1       0
  464.12     .12       0
Bank Sta=235.1,274
XS Rating Curve= 0 ,0
Exp/Cntr(USF)=0,0
Exp/Cntr=0.3,0.1

Type RM Length L Ch R = 1 ,1460    ,,,
XS GIS Cut Line= 4
2197550.76811301480774.6910657992197195.89161339480768.404764361
2197050.81586952481219.2368664832197183.39818824481489.819594629
#Sta/Elev= 30
       0 3050.16    50.6 3040.89    54.6 3039.77    70.6 3030.97    86.6 3029.81
   102.6 3030.39   118.6 3027.03   130.6 3026.34   162.6 3012.35   166.6 3011.65
   202.6 3009.61   354.6 3006.72   385.2 3006.65   445.4    3009   476.1 3007.87
   557.4  3008.4   561.6 3007.63  563.04 3006.17     570 3003.64   582.7 3003.62
   591.1 3004.08   595.3 3006.04   599.5 3008.23   603.7 3008.48   628.9 3007.71
   666.7 3009.74   780.1 3009.38   826.4 3016.38   977.1 3017.41  1129.9 3016.71
#Mann= 7 ,-1,0
       0      .1       0  364.93     .08       0  563.04    .045       0
   595.3     .08       0  624.93      .1       0  684.93     .06       0
  824.93     .12       0
#XS Ineff= 2 , 0
           445.2 3014.93
Permanent Ineff=
       F       F
Bank Sta=563.04,595.3
XS Rating Curve= 0 ,0
Exp/Cntr=0.3,0.1
LCMann Table=0

Chan Stop Cuts=-1
Use User Specified Reach Order=0
Composite Channel Slope=5